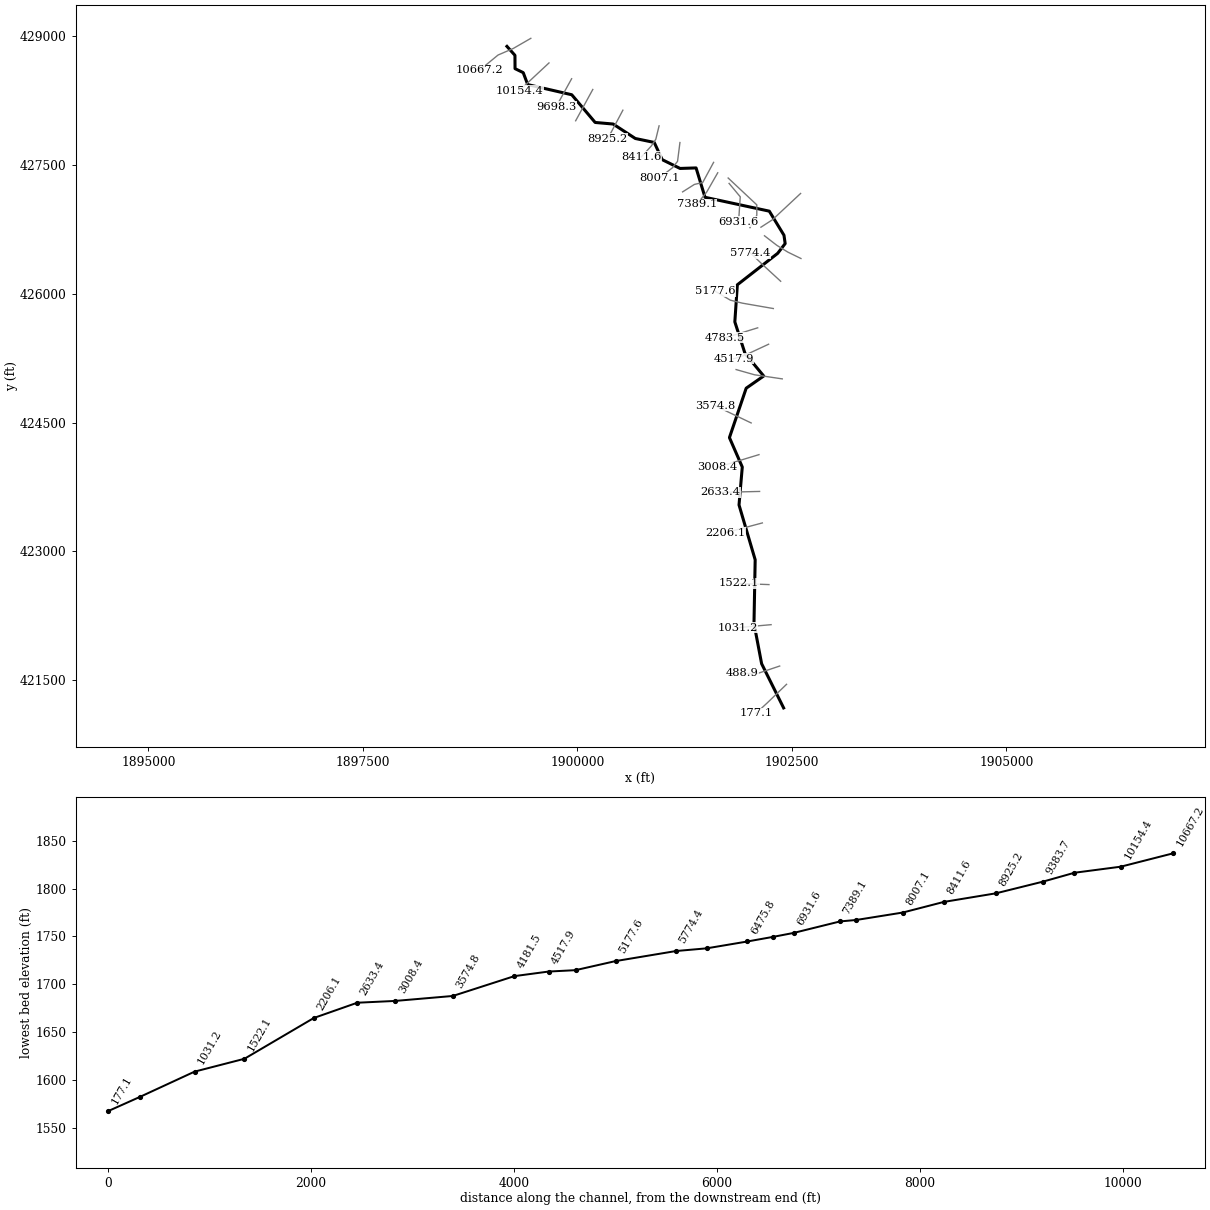
--- LILAURELRN.prj (project) ---

Proj Title=LILAURELRN
Current Plan=p01
Default Exp/Contr=0,0
English Units
Geom File=g01
Flow File=f01
Plan File=p01
BEGIN DESCRIPTION:
END DESCRIPTION:
DSS Export Rating Curves= 0
DSS Export Rating Curve Sorted= 0
DSS Export Volume Flow Curves= 0
DXF OffsetX= 0
DXF OffsetY= 0
DXF ScaleX= 0
DXF ScaleY= 0

--- LILAURELRN.p01 (plan) ---

Plan Title=Floodplain
Program Version=4.00
Geom File=g01
Flow File=f01
K Sum by GR=0
Std Step Tol=0.01
Critical Tol=0.01
Num of Std Step Trials=20
Max Error Tol=0.3
Flow Tol Ratio=0.001
Split Flow NTrial=30
Split Flow Tol=0.02
Split Flow Ratio=0.02
Log Output Level=0
Friction Slope Method=1
Unsteady Friction Slope Method=2
Unsteady Bridges Friction Slope Method=1
Global Log Level=0
CheckData=False
Run HTab=0
Run UNet=0
Run PostProcess=0
UNET Theta=0
UNET Theta Warmup=0
UNET ZTol=0
UNET ZSATol=0
UNET MxIter=0
UNET MaxInSteps=0
UNET DtIC=0
UNET DtMin=0
UNET MaxCRTS=0
UNET WFStab=0
UNET SFStab=0
UNET WFX=0
UNET SFX=0
UNET DSS MLevel=0
UNET DZMax Abort=0
UNET Convert EG Bridges=0
UNET Use Existing IB Tables=0
UNET Froude Limit=0
UNET Froude Power=0
Write IC File=0
Echo Input=False
Echo Output=False
Write Detailed=0

--- LILAURELRN.f01 (steady flow) ---

Flow Title=NFF Regression Equation
Program Version=4.10
Number of Profiles= 1
Profile Names=P100yr
River Rch & RM=LILAURELRN,Main            ,10667.2
536.0433
River Rch & RM=LILAURELRN,Main            ,6725.9
571.9774
River Rch & RM=LILAURELRN,Main            ,6075.3
680.9319
River Rch & RM=LILAURELRN,Main            ,3574.8
753.8753
River Rch & RM=LILAURELRN,Main            ,3008.4
 802.549
River Rch & RM=LILAURELRN,Main            ,488.9
859.4125
Boundary for River Rch & Prof#=LILAURELRN,Main            , 1
Up Type= 0
Dn Type= 1
Dn Known WS=1570.7
DSS Import GetInterval= 0
DSS Import GetPeak= 0
DSS Import FillOption= 0

--- LILAURELRN.g01 (geometry) ---

Geom Title=USGS 10m DEM
Program Version=4.10

River Reach=LILAURELRN      ,Main
Reach XY= 30
     1899178.456      428880.995     1899271.772      428776.829
     1899272.857      428621.664     1899368.343      428575.006
     1899420.644        428435.9     1899933.882      428317.627
     1900206.625      427994.928     1900415.826      427976.698
     1900674.507      427808.296     1900894.993      427762.289
     1900987.875      427561.768     1901196.208      427459.337
      1901382.84      427465.414     1901487.007        427123.4
     1902236.139      426961.941     1902407.146      426681.559
     1902421.034      426584.337     1902333.462      426470.472
     1901863.743       426104.52     1901834.446      425672.662
     1901952.718      425305.908     1902170.817      425042.237
     1901966.824      424900.092     1901771.512      424324.812
     1901921.251      423982.124     1901883.274        423540.5
      1902071.58      422902.187     1902057.683      422160.326
     1902146.702      421691.521     1902403.027      421176.906

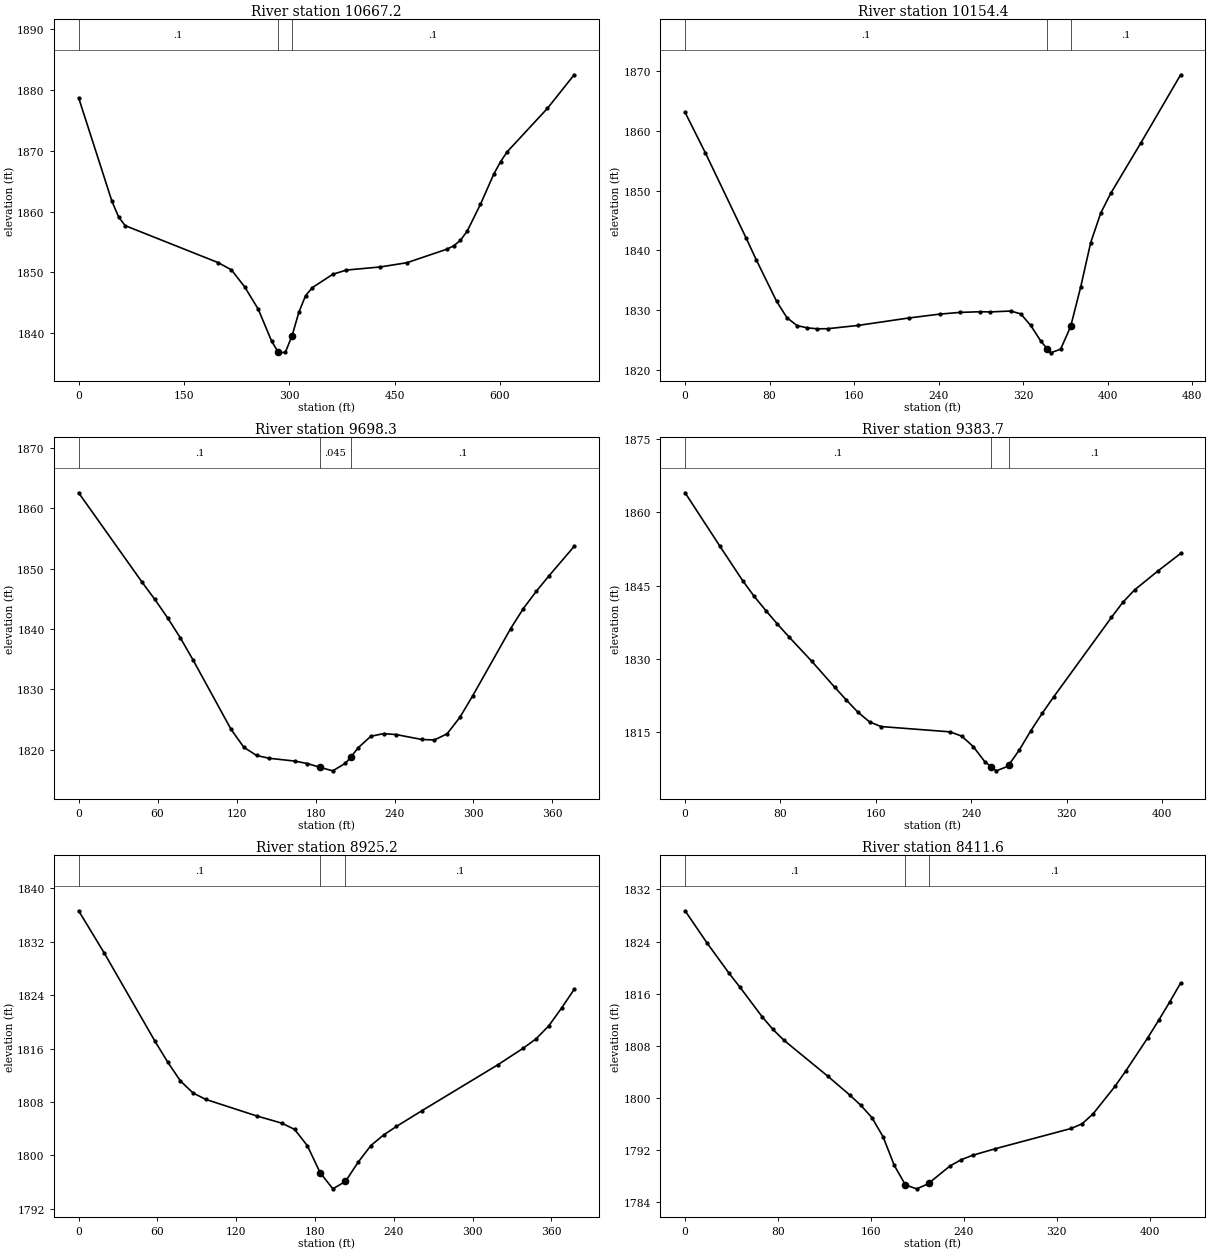
Type RM Length L Ch R = 1 ,10667.2 ,504.2,512.7,519.9
XS GIS Cut Line= 4
     1899456.791      428974.622      1899251.93      428856.567
     1899074.847      428780.178     1898861.305      428604.831
#Sta/Elev= 30
       0 1878.75    47.3 1861.75    56.8 1859.15    66.2  1857.7   198.6 1851.61
   217.5 1850.42   236.4 1847.62   255.7 1843.95     275 1838.62  283.76 1836.95
   284.7 1836.75   294.3 1836.83   303.9 1839.56   313.6 1843.44   323.2 1846.18
   332.9  1847.5   361.8 1849.68   381.1 1850.38   429.3 1850.89   467.4 1851.59
   524.6 1853.83   534.1 1854.38   543.6 1855.27   553.2 1856.78   572.2 1861.22
   591.3 1866.22   600.8 1868.23   610.3 1869.87   667.5 1877.01   705.6 1882.54
#Mann= 3 , 0 , 0
       0      .1       0  283.76    .045       0   303.9      .1       0
Bank Sta=283.76,303.9
XS Rating Curve= 0 ,0
Exp/Cntr=0.3,0.1

Type RM Length L Ch R = 1 ,10154.4 ,448.5,456.1,462.6
XS GIS Cut Line= 3
     1899668.597      428688.164     1899442.902      428478.095
     1899326.583      428366.983
#Sta/Elev= 30
       0 1863.11    19.3  1856.3    57.8 1842.07    67.4 1838.43    86.7 1831.47
    96.4 1828.75     106 1827.42   115.6 1827.05   125.3 1826.88   134.9  1826.9
   163.8 1827.45     212  1828.7   240.9 1829.34   260.2 1829.63   279.4 1829.74
   289.1 1829.71   308.3 1829.86   317.8 1829.38   327.2 1827.46   336.7 1824.85
  342.87 1823.53   346.2 1822.86   355.6 1823.48   365.1 1827.29   374.6 1833.91
     384 1841.29   393.5 1846.24     403 1849.56   431.3 1857.93   469.2 1869.41
#Mann= 3 , 0 , 0
       0      .1       0  342.87    .045       0   365.1      .1       0
#XS Ineff= 2 , 0
          314.73 1828.87
Permanent Ineff=
       F       F
Bank Sta=342.87,365.1
XS Rating Curve= 0 ,0
Exp/Cntr=0.3,0.1

Type RM Length L Ch R = 1 ,9698.3  ,315.3,314.6,313.5
XS GIS Cut Line= 2
     1899932.385      428504.206     1899750.294      428174.639
#Sta/Elev= 30
       0 1862.55    48.3 1847.72    57.9  1844.9    67.6 1841.85    77.2 1838.56
    86.9 1834.89   115.8 1823.39   125.5 1820.43   135.2 1819.06   144.8  1818.6
   164.1 1818.14   173.8 1817.73   183.4 1817.09   193.1 1816.52   202.7 1817.77
   206.6 1818.75   212.4 1820.34     222 1822.24   231.7 1822.68   241.4 1822.52
   260.7 1821.71   270.3 1821.63     280 1822.66   289.6 1825.36   299.3  1828.9
   328.2 1840.06   337.9 1843.39   347.6 1846.21   357.2 1848.76   376.5 1853.68
#Mann= 3 , 0 , 0
       0      .1       0   183.4    .045       0   206.6      .1       0
Bank Sta=183.4,206.6
XS Rating Curve= 0 ,0
Exp/Cntr=0.3,0.1

Type RM Length L Ch R = 1 ,9383.7  ,457.7,458.5,458.3
XS GIS Cut Line= 2
     1900179.013      428379.136     1899979.361      428014.553
#Sta/Elev= 30
       0 1864.02      29 1853.16    48.3 1846.03      58  1842.8    67.7 1839.92
    77.3 1837.19      87 1834.56   106.3 1829.52   125.7 1824.16   135.3 1821.59
     145  1819.1   154.7 1817.12   164.3 1816.17   222.3 1815.08     232 1814.21
   241.7 1812.08   251.3 1809.01   256.7 1807.95     261  1807.1   270.7 1808.02
   271.7 1808.37   280.3 1811.34     290  1815.3   299.7 1818.92   309.3 1822.27
   357.7 1838.53   367.3 1841.62     377 1844.12   396.3 1847.95   415.7  1851.6
#Mann= 3 , 0 , 0
       0      .1       0   256.7    .045       0   271.7      .1       0
Bank Sta=256.7,271.7
XS Rating Curve= 0 ,0
Exp/Cntr=0.3,0.1

Type RM Length L Ch R = 1 ,8925.2  ,515.7,513.6,510.7
XS GIS Cut Line= 2
     1900529.708      428137.817     1900352.624      427804.483
#Sta/Elev= 25
       0  1836.6    19.4 1830.32    58.1  1817.1    67.8 1813.98    77.4 1811.18
    87.1 1809.35    96.8 1808.39   135.5 1805.92   154.8 1804.83   164.5  1803.9
   174.2 1801.46   183.9 1797.44   193.6 1795.01   203.2 1796.11   212.9    1799
   222.6 1801.49   232.3 1803.07     242 1804.34   261.3 1806.68   319.4 1813.58
   338.7 1816.06   348.4 1817.45   358.1  1819.4   367.8 1822.05   377.4 1824.85
#Mann= 3 , 0 , 0
       0      .1       0   183.9    .045       0   203.2      .1       0
Bank Sta=183.9,203.2
XS Rating Curve= 0 ,0
Exp/Cntr=0.3,0.1

Type RM Length L Ch R = 1 ,8411.6  ,406.1,404.5,403
XS GIS Cut Line= 4
     1900951.583      427955.525     1900913.388      427799.275
     1900859.569      427719.414     1900744.986      427594.414
#Sta/Elev= 30
       0 1828.73    18.9 1823.78    37.8 1819.14    47.3 1816.97    66.2 1812.48
    75.7 1810.49    85.2 1808.82     123 1803.29   141.9  1800.4   151.4 1798.82
   160.8 1796.96   170.5 1793.99   180.1 1789.61   189.7  1786.6   199.4    1786
     209 1786.74     210 1786.89   228.3 1789.54   237.9 1790.49   247.5 1791.15
   266.6 1792.14   332.5 1795.28   341.9    1796   351.4 1797.54   370.2 1801.76
   379.6 1804.15   398.5 1809.24   407.9 1811.93   417.3 1814.72   426.7 1817.63
#Mann= 3 , 0 , 0
       0      .1       0   189.7    .045       0     210      .1       0
Bank Sta=189.7,210
XS Rating Curve= 0 ,0
Exp/Cntr=0.3,0.1

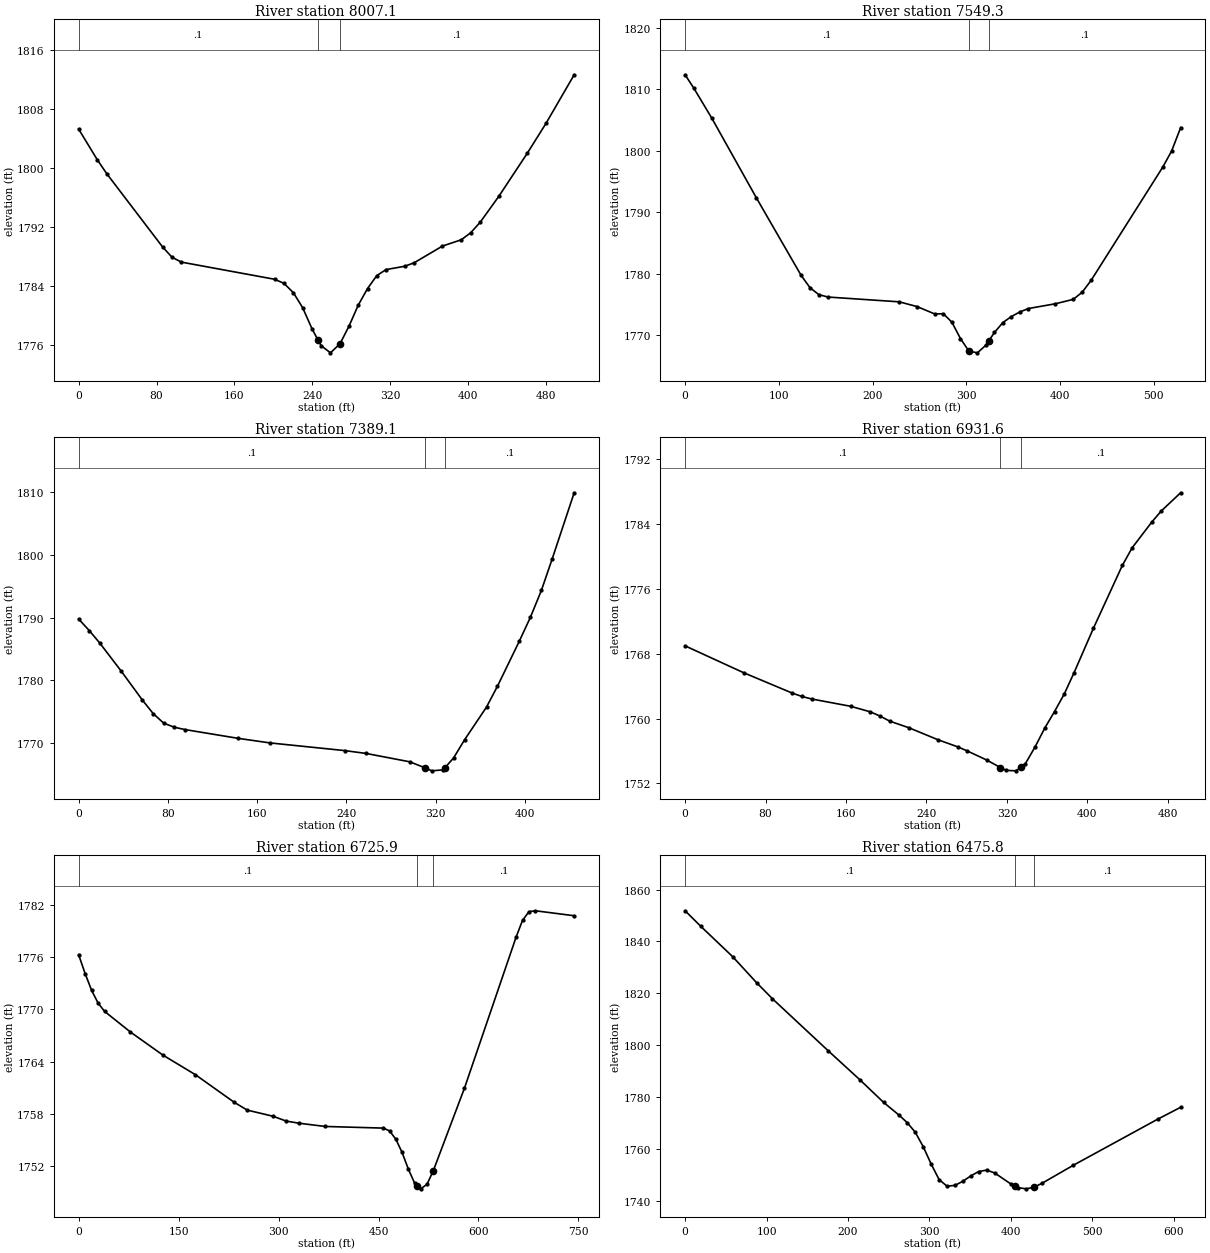
Type RM Length L Ch R = 1 ,8007.1  ,472,457.8,441.2
XS GIS Cut Line= 4
     1901194.638      427761.081     1901166.861      427542.331
     1901107.833      427467.678     1900955.055      427349.622
#Sta/Elev= 30
       0 1805.25    19.2 1801.08    28.8 1799.21    86.3 1789.24    95.9 1787.86
   105.5  1787.2   201.3 1784.87   210.9 1784.31   220.5 1783.05     230 1781.02
   239.5 1778.19  245.67 1776.64   249.1 1775.85   258.6 1774.89   268.4 1776.13
   277.6 1778.51   287.1 1781.36   296.6 1783.61   306.2 1785.38   315.7 1786.19
     335 1786.64   344.6 1787.12   373.6 1789.38   392.9 1790.23   402.6 1791.19
   412.2 1792.59   431.5 1796.14   460.5 1801.94   479.8 1806.01   508.8 1812.62
#Mann= 3 , 0 , 0
       0      .1       0  245.67    .045       0   268.4      .1       0
Bank Sta=245.67,268.4
XS Rating Curve= 0 ,0
Exp/Cntr=0.3,0.1

Type RM Length L Ch R = 1 ,7549.3  ,144.5,160.2,174.7
XS GIS Cut Line= 4
     1901586.999      427530.178     1901460.263      427295.803
     1901363.041      427273.233     1901225.888      427186.428
#Sta/Elev= 30
       0 1812.36     9.5 1810.13    28.6 1805.27    76.1 1792.32   123.7 1779.74
   133.2 1777.72   142.7 1776.59   152.3  1776.2   228.4 1775.42   247.4 1774.65
   266.4 1773.44   275.5 1773.49   284.6  1772.1   293.7 1769.45   302.7 1767.41
   311.8 1767.12   320.9 1768.37   324.2 1769.12     330 1770.44     339 1772.05
   348.1 1773.03   357.2 1773.78   366.2 1774.33   394.9  1775.1     414 1775.82
   423.5 1776.97   433.1 1778.91   509.5 1797.33     519 1799.96   528.6 1803.76
#Mann= 3 , 0 , 0
       0      .1       0   302.7    .045       0   324.2      .1       0
Bank Sta=302.7,324.2
XS Rating Curve= 0 ,0
Exp/Cntr=0.3,0.1

Type RM Length L Ch R = 1 ,7389.1  ,443,457.5,471.1
XS GIS Cut Line= 3
     1901635.177      427408.867     1901507.138      427185.343
     1901389.951      427039.943
#Sta/Elev= 27
       0  1789.8     9.5 1787.97    19.1 1785.94    38.2 1781.49    57.2 1776.87
    66.8 1774.73    76.3 1773.19    85.9 1772.54    95.4 1772.17   143.1 1770.77
   171.7 1770.04   238.5 1768.82   257.6 1768.37   296.9 1767.03   310.6 1766.07
   316.6 1765.59   326.4 1765.74  328.42 1766.08   336.2 1767.65   346.1 1770.56
   365.7 1775.76   375.5 1779.08   395.2  1786.3     405 1790.06   414.9 1794.36
   424.7 1799.45   444.3 1809.94
#Mann= 3 , 0 , 0
       0      .1       0   310.6    .045       0  328.42      .1       0
Bank Sta=310.6,328.42
XS Rating Curve= 0 ,0
Exp/Cntr=0.3,0.1

Type RM Length L Ch R = 1 ,6931.6  ,202.9,205.7,206
XS GIS Cut Line= 3
     1901767.555      427285.169     1901897.763      427128.919
     1901878.232      426840.291
#Sta/Elev= 30
       0 1768.99    58.1 1765.68   106.5 1763.16   116.2 1762.74   125.9 1762.43
   164.6 1761.53     184 1760.85   193.7 1760.33   203.4  1759.7   222.7 1758.87
   251.6 1757.39   270.9 1756.53   280.5 1756.02   299.8  1754.9  313.59 1753.96
   319.1 1753.62   328.8 1753.56   334.2 1754.02   338.4 1754.46     348 1756.52
   357.7 1758.86   367.3 1760.88     377 1763.05   386.6 1765.64   405.9 1771.14
   434.8 1778.94   444.5  1781.1   463.8 1784.24   473.4 1785.64   492.7 1787.89
#Mann= 3 , 0 , 0
       0      .1       0  313.59    .045       0   334.2      .1       0
Bank Sta=313.59,334.2
XS Rating Curve= 0 ,0
Exp/Cntr=0.3,0.1

Type RM Length L Ch R = 1 ,6725.9  ,268.4,250.1,231.3
XS GIS Cut Line= 4
     1901756.704      427348.103     1902090.472      427035.386
     1902090.472      426913.858     1902010.611      426769.761
#Sta/Elev= 30
       0 1776.28     9.7 1774.12    19.5 1772.18    29.2 1770.72    38.9 1769.77
    77.8 1767.39   126.5 1764.74   175.2 1762.49   233.6 1759.31     253 1758.42
   291.9 1757.71   311.4 1757.16   330.9 1756.91   369.8 1756.54   457.4 1756.35
   466.7 1756.02   476.1 1755.06   485.4 1753.55   494.8 1751.63   504.1 1750.04
  508.36  1749.7   513.5 1749.37   522.8  1749.9   532.2 1751.45   578.9 1760.93
   656.4 1778.29   666.1 1780.23   675.8 1781.23   685.5 1781.33   743.6 1780.76
#Mann= 3 , 0 , 0
       0      .1       0  508.36    .045       0   532.2      .1       0
Bank Sta=508.36,532.2
XS Rating Curve= 0 ,0
Exp/Cntr=0.3,0.1

Type RM Length L Ch R = 1 ,6475.8  ,430.2,400.5,370.7
XS GIS Cut Line= 3
     1902600.888      427167.982     1902273.197      426861.992
     1902138.649      426775.187
#Sta/Elev= 30
       0  1851.8    19.5 1845.74    58.5 1834.08    87.7 1824.11   107.2  1817.9
   175.4 1797.92   214.4 1786.71   243.7 1777.95   263.2 1772.89   272.9 1770.07
   282.6 1766.43   292.4 1760.86   302.1 1754.19   311.9 1748.18   321.6 1745.62
   331.4 1745.94   341.1 1747.52   350.9 1749.61   360.6 1751.28   370.4 1751.82
   380.1 1750.74   399.6 1746.56  405.57 1745.59   409.4 1745.03   419.1  1744.6
   428.8 1745.27   438.6  1746.8   476.6 1753.67   580.2 1771.43   608.5 1776.04
#Mann= 3 , 0 , 0
       0      .1       0  405.57    .045       0   428.8      .1       0
#XS Ineff= 2 , 0
          370.16 1751.48
Permanent Ineff=
       F       F
Bank Sta=405.57,428.8
XS Rating Curve= 0 ,0
Exp/Cntr=0.3,0.1

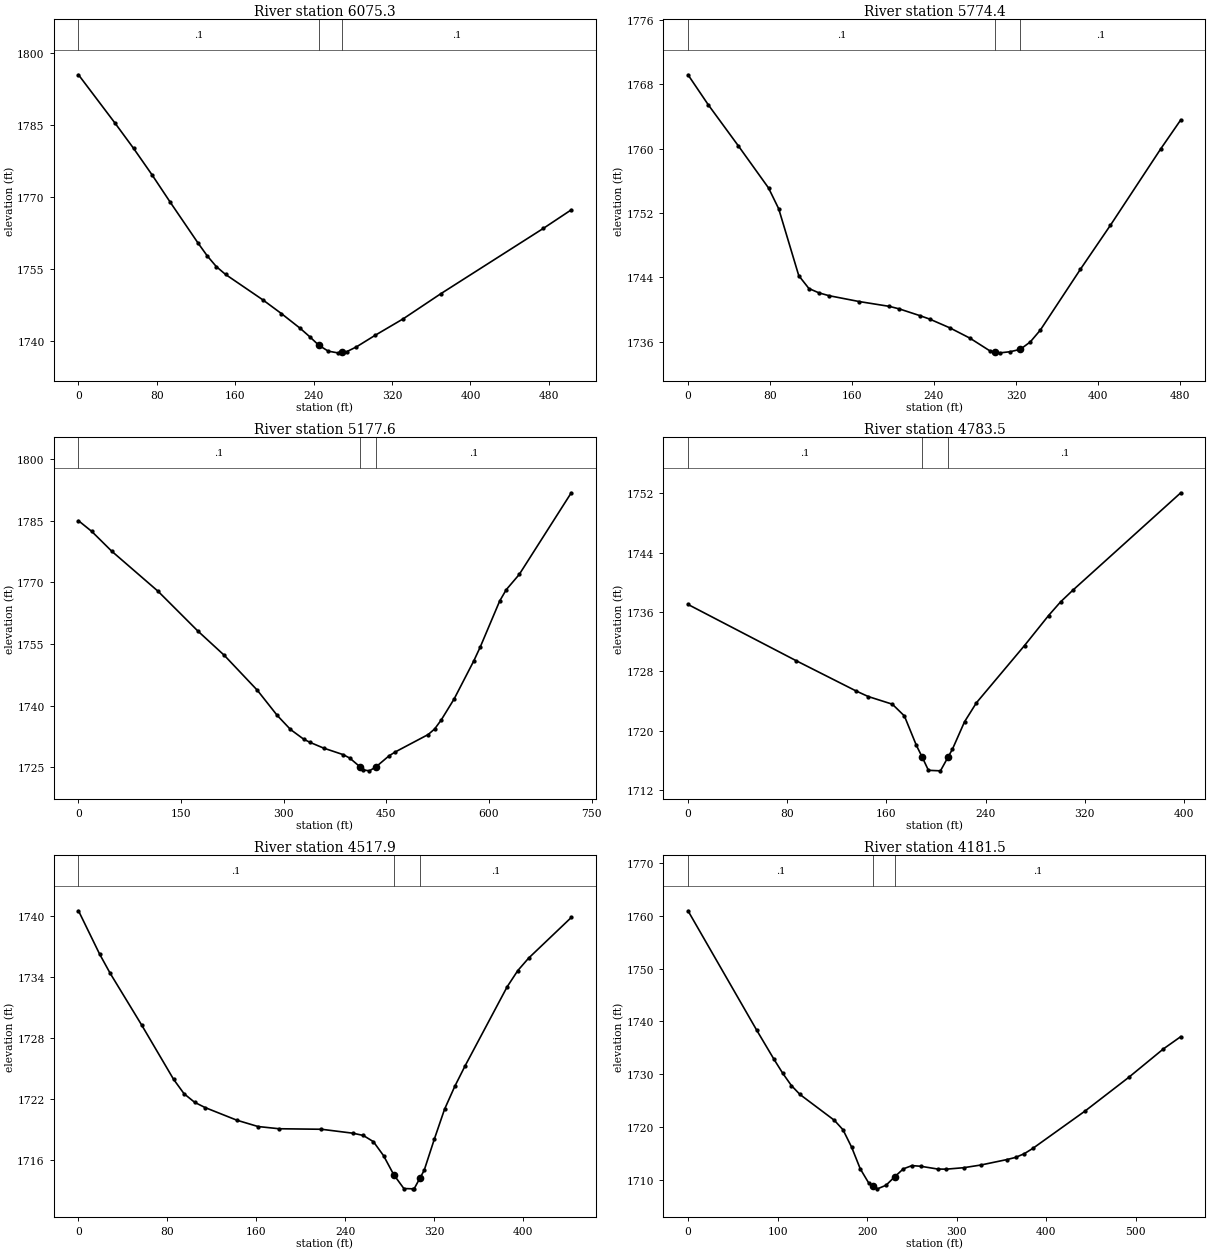
Type RM Length L Ch R = 1 ,6075.3  ,305.5,300.9,296
XS GIS Cut Line= 4
     1902605.229      426410.603     1902453.319      426484.388
     1902323.111      426564.683     1902179.881       426675.36
#Sta/Elev= 24
       0 1795.54    37.5 1785.38    56.3 1780.14    75.1 1774.62    93.8 1768.86
     122 1760.38   131.4  1757.7   140.7 1755.45   150.1 1753.82     188 1748.53
   207.1 1745.64   226.2 1742.57   235.8 1740.84   245.4    1739   254.9 1737.79
   264.5 1737.44  269.42 1737.59     274 1737.71   283.6 1738.68   302.7  1741.1
   331.4 1744.55   369.5 1749.76   474.3 1763.43   502.9 1767.32
#Mann= 3 , 0 , 0
       0      .1       0   245.4    .045       0  269.42      .1       0
Bank Sta=245.4,269.42
XS Rating Curve= 0 ,0
Exp/Cntr=0.3,0.1

Type RM Length L Ch R = 1 ,5774.4  ,585.3,596.8,608.7
XS GIS Cut Line= 3
     1902368.683      426145.412     1902173.371        426325.1
     1902017.121      426473.537
#Sta/Elev= 27
       0 1769.18    19.7 1765.47    49.2 1760.34    78.6 1755.12    88.5 1752.54
   108.1 1744.23     118 1742.63   127.8 1742.09   137.6 1741.74   167.1 1741.01
   196.6 1740.41   206.4 1740.09   226.1 1739.27   235.9 1738.83   255.6 1737.74
   275.2 1736.46   294.8 1734.87  299.75 1734.73   304.6 1734.64   314.4 1734.78
   324.2 1735.07     334 1735.99   343.8 1737.46     383 1745.03   412.3  1750.5
   461.3 1759.97   480.9 1763.58
#Mann= 3 , 0 , 0
       0      .1       0  299.75    .045       0   324.2      .1       0
Bank Sta=299.75,324.2
XS Rating Curve= 0 ,0
Exp/Cntr=0.3,0.1

Type RM Length L Ch R = 1 ,5177.6  ,380.6,394.1,406.3
XS GIS Cut Line= 4
      1902283.18      425827.921     1901920.767      425890.855
     1901781.878      425925.577     1901601.756      426031.914
#Sta/Elev= 30
       0 1784.98    19.4 1782.37    48.4 1777.59   116.2 1767.82   174.2 1758.17
     213 1752.23   261.4 1743.71   290.4  1737.6   309.8 1734.17   329.1 1731.81
   338.8    1731   358.2 1729.64   386.9 1728.04   396.5  1727.2  411.35 1725.09
   415.6 1724.34   425.1  1724.1   434.6 1725.04   453.7 1727.73   463.3 1728.73
     511 1732.93   520.5 1734.29     530 1736.45     549  1741.6   577.6 1750.82
   587.1 1754.22   615.6 1765.45   625.1 1768.18   644.1 1771.89   720.2 1791.78
#Mann= 3 , 0 , 0
       0      .1       0  411.35    .045       0   434.6      .1       0
Bank Sta=411.35,434.6
XS Rating Curve= 0 ,0
Exp/Cntr=0.3,0.1

Type RM Length L Ch R = 1 ,4783.5  ,263,265.6,267.6
XS GIS Cut Line= 2
     1902100.888      425603.312     1901721.114      425486.124
#Sta/Elev= 19
       0 1737.01    87.2 1729.44   135.7 1725.35   145.4 1724.61   164.8 1723.58
   174.5    1722   184.2 1718.03  188.72 1716.51   193.9 1714.68   203.6 1714.61
  209.59 1716.42   213.3 1717.54     223 1721.21   232.6 1723.77   271.4 1731.48
   290.8 1735.52   300.5 1737.36   310.2  1738.9   397.4 1752.04
#Mann= 3 , 0 , 0
       0      .1       0  188.72    .045       0  209.59      .1       0
Bank Sta=188.72,209.59
XS Rating Curve= 0 ,0
Exp/Cntr=0.3,0.1

Type RM Length L Ch R = 1 ,4517.9  ,348.3,336.4,324
XS GIS Cut Line= 4
     1902228.058      425412.339       1902004.1      425308.173
     1901902.538      425266.506     1901819.204      425243.068
#Sta/Elev= 30
       0  1740.5      19 1736.24    28.5 1734.35      57 1729.23    85.5 1723.93
      95  1722.5   104.5 1721.66     114 1721.14   142.5  1719.9   161.5 1719.28
   180.5 1719.06   218.5 1719.01     247 1718.62   256.2  1718.4   265.3 1717.79
   274.4 1716.42   283.6 1714.54   292.7 1713.18     301 1713.15   301.9 1713.15
  307.24 1714.22     311 1714.98   320.2 1718.07   329.3 1720.98   338.5 1723.23
   347.6 1725.21   385.6 1733.02   395.2 1734.62   404.9 1735.84   443.3 1739.84
#Mann= 3 , 0 , 0
       0      .1       0   283.6    .045       0  307.24      .1       0
Bank Sta=283.6,307.24
XS Rating Curve= 0 ,0
Exp/Cntr=0.3,0.1

Type RM Length L Ch R = 1 ,4181.5  ,613.4,606.7,599.3
XS GIS Cut Line= 3
     1902387.347      425008.693     1902063.996      425056.437
     1901849.152        425117.2
#Sta/Elev= 30
       0 1760.92    76.9  1738.3    96.1 1732.83   105.8 1730.21   115.4  1727.9
     125 1726.21   163.4 1721.33     173 1719.55   182.7 1716.24   192.3 1712.16
   201.9 1709.44  206.65 1708.89   211.5 1708.38   221.1 1709.06   230.7 1710.65
   240.3 1712.15     250 1712.77   259.6 1712.65   278.8 1712.12   288.4  1712.1
   307.6 1712.37   326.9 1712.88     356 1713.91   365.7 1714.32   375.4 1715.02
   385.1 1716.04   443.4  1723.1   491.9 1729.43   530.7 1734.82   550.1 1737.14
#Mann= 3 , 0 , 0
       0      .1       0  206.65    .045       0   230.7      .1       0
Bank Sta=206.65,230.7
XS Rating Curve= 0 ,0
Exp/Cntr=0.3,0.1

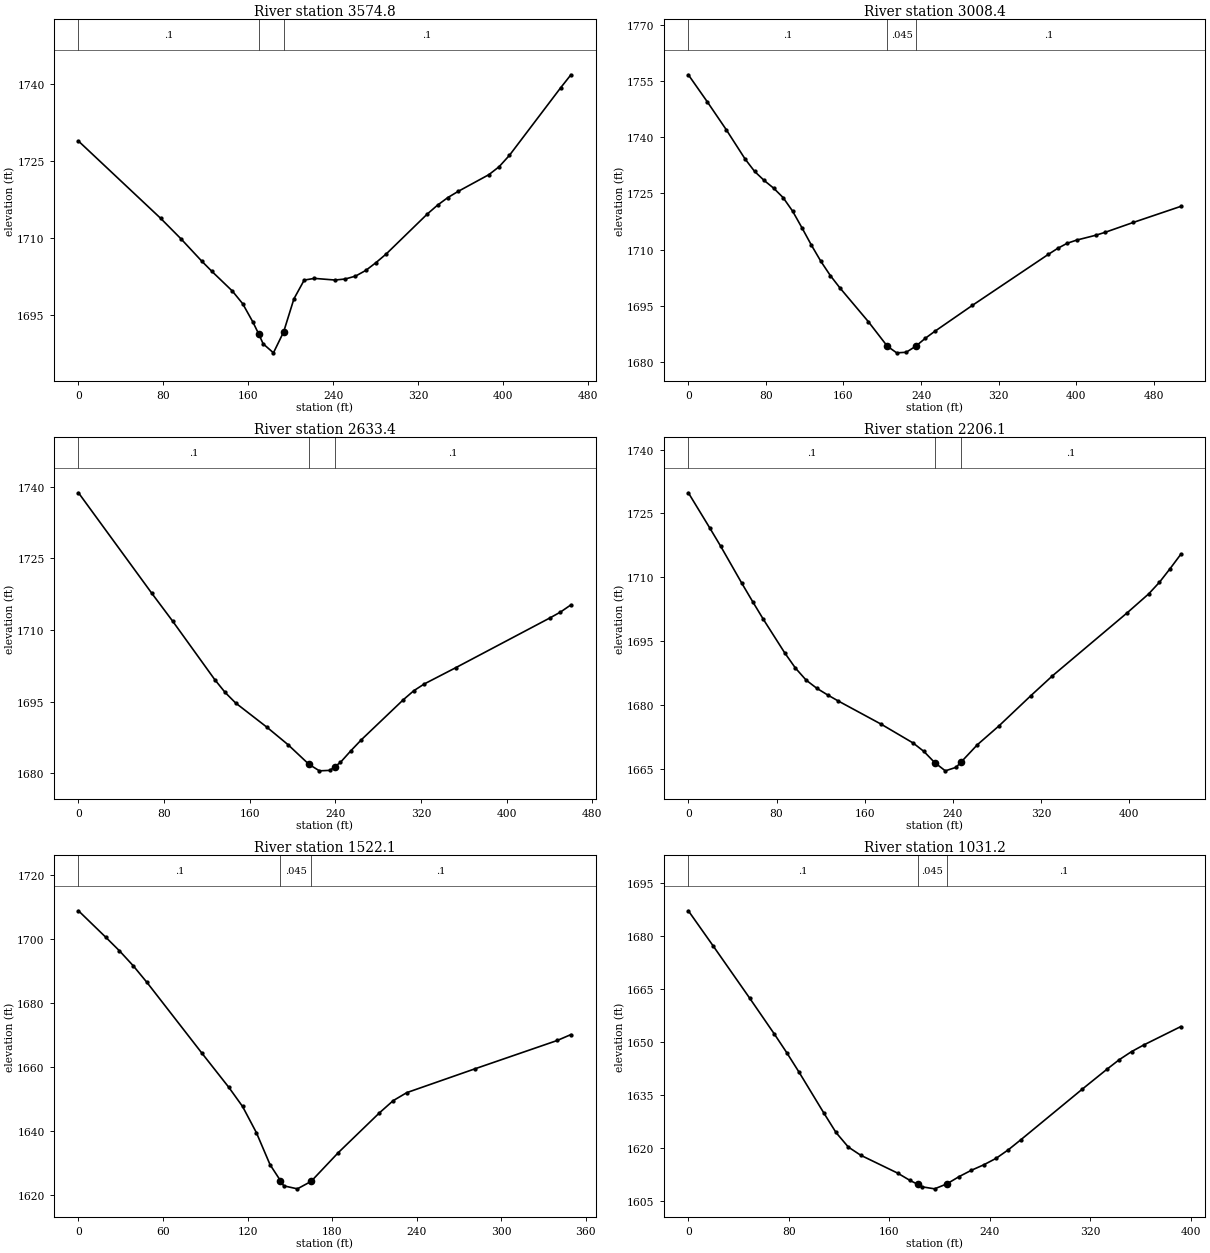
Type RM Length L Ch R = 1 ,3574.8  ,549.5,566.5,582.8
XS GIS Cut Line= 2
     1902024.933      424495.456     1901606.097      424695.108
#Sta/Elev= 30
       0 1728.91    77.3 1713.87    96.7 1709.82     116 1705.53   125.7  1703.5
     145 1699.66   154.7  1697.2   164.3 1693.63  169.95 1691.24     174 1689.37
   183.7 1687.61   193.3 1691.69     203 1698.14   212.7  1701.8   222.3 1702.13
   241.7 1701.81   251.3 1702.01     261 1702.57   270.7 1703.68   280.3  1705.2
     290  1706.9   328.7 1714.69   338.3 1716.41     348 1717.89   357.7 1719.09
   386.7 1722.36   396.3  1723.9     406 1726.11   454.3  1739.3     464 1741.84
#Mann= 3 , 0 , 0
       0      .1       0  169.95    .045       0   193.3      .1       0
Bank Sta=169.95,193.3
XS Rating Curve= 0 ,0
Exp/Cntr=0.3,0.1

Type RM Length L Ch R = 1 ,3008.4  ,380.8,374.9,369.1
XS GIS Cut Line= 2
     1902116.079      424126.532     1901629.968      423978.963
#Sta/Elev= 30
       0 1756.66    19.5 1749.46    39.1    1742    58.6 1734.15    68.4 1730.85
    78.2 1728.45    87.9 1726.41    97.7 1723.89   107.5 1720.28   117.2 1715.81
     127 1711.15   136.8 1706.82   146.5 1703.05   156.3 1699.78   185.6 1690.78
   205.2 1684.22   214.9 1682.43   224.7 1682.58   234.7 1684.21   244.2 1686.27
     254 1688.13   293.1 1695.12   371.2 1708.69     381 1710.32   390.8 1711.68
   400.6 1712.53   420.1 1713.81   429.9  1714.6   459.2 1717.26     508 1721.53
#Mann= 3 , 0 , 0
       0      .1       0   205.2    .045       0   234.7      .1       0
Bank Sta=205.2,234.7
XS Rating Curve= 0 ,0
Exp/Cntr=0.3,0.1

Type RM Length L Ch R = 1 ,2633.4  ,422.2,427.4,432.4
XS GIS Cut Line= 2
     1902123.024       423697.93     1901662.954      423687.079
#Sta/Elev= 22
       0 1738.71    68.5 1717.69    88.1 1711.83   127.3 1699.64   137.1 1696.93
   146.9 1694.73   176.2 1689.65   195.8 1686.02   215.4  1681.9   225.2 1680.54
     235 1680.64  239.59  1681.4   244.8 1682.31   254.6 1684.75   264.4 1687.05
   303.5  1695.4   313.3 1697.29   323.1 1698.71   352.5 1702.11   440.6 1712.53
   450.4 1713.75   460.2 1715.26
#Mann= 3 , 0 , 0
       0      .1       0   215.4    .045       0  239.59      .1       0
Bank Sta=215.4,239.59
XS Rating Curve= 0 ,0
Exp/Cntr=0.3,0.1

Type RM Length L Ch R = 1 ,2206.1  ,690.2,684,676.9
XS GIS Cut Line= 2
     1902155.142      423331.176     1901723.284      423216.159
#Sta/Elev= 28
       0 1729.85    19.4 1721.61    29.2 1717.37    48.6 1708.58    58.3 1704.33
      68 1700.18    87.4  1692.3    97.2  1688.7   106.9 1685.88   116.6 1683.96
   126.3 1682.42     136 1680.99   174.9 1675.55     204 1671.12   213.7 1669.16
   223.5 1666.54   233.2 1664.59   242.9 1665.41   247.3 1666.59   262.3 1670.72
   281.8 1675.12   310.9 1682.25   330.3 1686.86   398.3 1701.69   417.8 1706.13
   427.5 1708.84   437.2 1712.05   446.9 1715.41
#Mann= 3 , 0 , 0
       0      .1       0   223.5    .045       0   247.3      .1       0
Bank Sta=223.5,247.3
XS Rating Curve= 0 ,0
Exp/Cntr=0.3,0.1

Type RM Length L Ch R = 1 ,1522.1  ,488,490.9,493.7
XS GIS Cut Line= 2
     1902232.399      422613.077     1901883.006      422626.098
#Sta/Elev= 21
       0 1708.82    19.4 1700.54    29.1  1696.3    38.8 1691.67    48.6 1686.44
    87.4 1664.44   106.8 1653.59   116.5 1647.64   126.3 1639.47     136 1629.46
  143.42 1624.44   145.7 1622.84   155.4  1621.9   165.1 1624.21   184.5 1633.24
   213.7 1645.67   223.4 1649.46   233.1 1651.98   281.6 1659.44   339.9 1668.28
   349.6 1670.12
#Mann= 3 , 0 , 0
       0      .1       0  143.42    .045       0   165.1      .1       0
Bank Sta=143.42,165.1
XS Rating Curve= 0 ,0
Exp/Cntr=0.3,0.1

Type RM Length L Ch R = 1 ,1031.2  ,536.9,542.3,547.1
XS GIS Cut Line= 2
     1902257.138       422146.28     1901866.513      422111.558
#Sta/Elev= 28
       0 1687.03    19.6 1677.18      49 1662.26    68.6 1652.15    78.4 1646.92
    88.2 1641.41   107.8 1629.95   117.6 1624.38   127.4 1620.27   137.3 1617.95
   166.7  1612.9   176.5 1610.84  182.65 1609.74   186.3 1609.02   196.1 1608.46
   205.9 1609.86   215.7 1611.93   225.5 1613.72   235.3 1615.25   245.1 1617.08
   254.9 1619.51   264.7  1622.3   313.7 1636.62   333.3 1642.23   343.1 1644.93
     353 1647.24   362.8 1649.13   392.2 1654.31
#Mann= 3 , 0 , 0
       0      .1       0  182.65    .045       0   205.9      .1       0
Bank Sta=182.65,205.9
XS Rating Curve= 0 ,0
Exp/Cntr=0.3,0.1

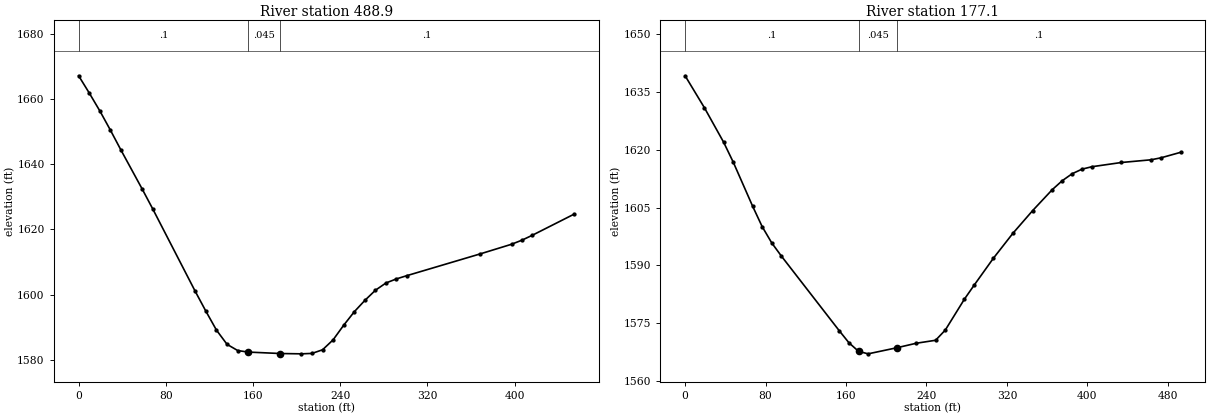
Type RM Length L Ch R = 1 ,488.9   ,301.4,311.8,322.4
XS GIS Cut Line= 3
     1902356.965      421664.509     1902098.718      421577.704
     1901916.427      421577.704
#Sta/Elev= 30
       0 1667.11     9.7 1661.85    19.5 1656.31    29.2 1650.41    38.9 1644.29
    58.4 1632.33    68.1 1626.22     107    1601   116.8 1594.89   126.5  1589.1
   136.2 1584.75     146 1582.84   155.7 1582.38   184.9 1581.94   204.3 1581.84
   214.1 1581.97   223.8 1583.08   233.5 1586.13   243.2 1590.61     253 1594.77
   262.7 1598.25   272.4 1601.36     282 1603.57   291.6 1604.82   301.2 1605.82
   368.4 1612.48   397.2 1615.44   406.8  1616.7   416.4 1618.22   454.7 1624.69
#Mann= 3 , 0 , 0
       0      .1       0   155.7    .045       0   184.9      .1       0
Bank Sta=155.7,184.9
XS Rating Curve= 0 ,0
Exp/Cntr=0.3,0.1

Type RM Length L Ch R = 1 ,177.1   ,176.5,177.2,176.7
XS GIS Cut Line= 3
      1902437.26      421451.836     1902209.395      421232.652
     1902079.187      421113.294
#Sta/Elev= 30
       0 1639.18    19.2 1630.89    38.3 1621.95    47.9 1616.76    67.1 1605.37
    76.6 1600.06    86.2  1595.8    95.8 1592.38   153.3 1573.03   162.9 1569.91
   172.5 1567.68     182 1567.03   210.8 1568.62   229.9 1569.78   249.1 1570.55
   258.7 1573.18   277.8 1581.23   287.4 1584.83   306.6 1591.84     326 1598.31
   345.6 1604.19   365.2 1609.65     375 1611.94   384.9 1613.76   394.7 1614.95
   404.5 1615.58   433.9 1616.68   463.4 1617.38   473.2 1617.89   492.8 1619.32
#Mann= 3 , 0 , 0
       0      .1       0   172.5    .045       0   210.8      .1       0
Bank Sta=172.5,210.8
XS Rating Curve= 0 ,0
Exp/Cntr=0.3,0.1

Chan Stop Cuts=-1
Use User Specified Reach Order=0
Composite Channel Slope=5